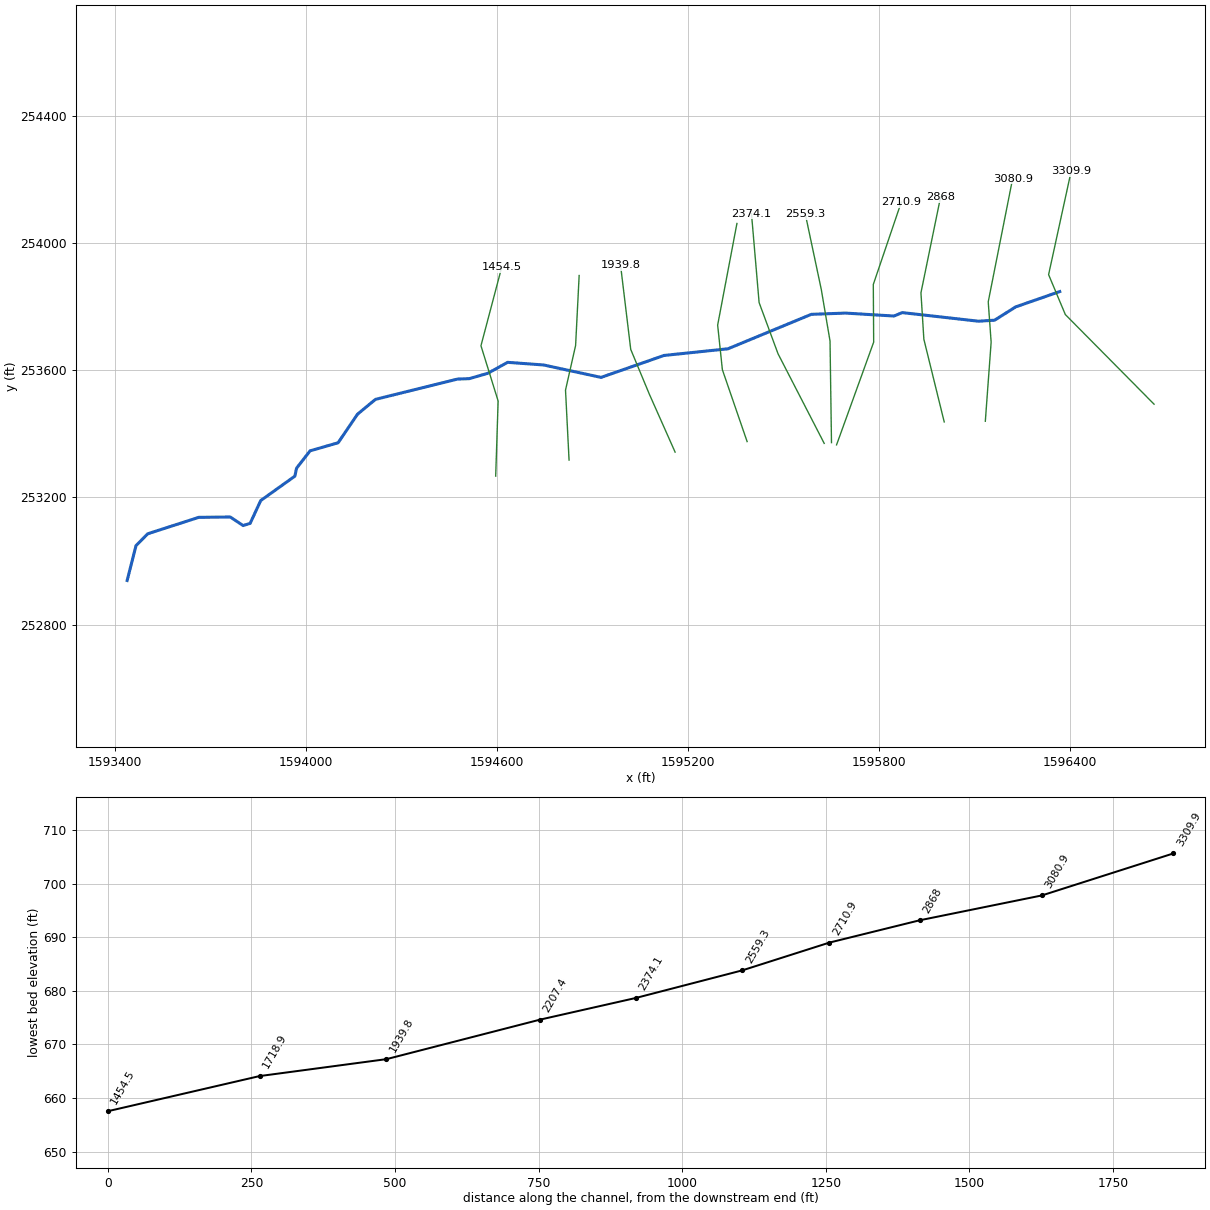
--- sgrtrcrk.prj (project) ---

Proj Title=sgrtrcrk
Current Plan=p01
Default Exp/Contr=0,0
English Units
Geom File=g01
Flow File=f01
Plan File=p01
BEGIN DESCRIPTION:
END DESCRIPTION:
DSS Export Rating Curves= 0
DSS Export Rating Curve Sorted= 0
DSS Export Volume Flow Curves= 0
DXF OffsetX= 0
DXF OffsetY= 0
DXF ScaleX= 0
DXF ScaleY= 0

--- sgrtrcrk.p01 (plan) ---

Plan Title=Floodplain
Program Version=4.00
Geom File=g01
Flow File=f01
K Sum by GR=0
Std Step Tol=0.01
Critical Tol=0.01
Num of Std Step Trials=20
Max Error Tol=0.3
Flow Tol Ratio=0.001
Split Flow NTrial=30
Split Flow Tol=0.02
Split Flow Ratio=0.02
Log Output Level=0
Friction Slope Method=1
Unsteady Friction Slope Method=2
Unsteady Bridges Friction Slope Method=1
Global Log Level=0
CheckData=False
Run HTab=0
Run UNet=0
Run PostProcess=0
UNET Theta=0
UNET Theta Warmup=0
UNET ZTol=0
UNET ZSATol=0
UNET MxIter=0
UNET MaxInSteps=0
UNET DtIC=0
UNET DtMin=0
UNET MaxCRTS=0
UNET WFStab=0
UNET SFStab=0
UNET WFX=0
UNET SFX=0
UNET DSS MLevel=0
UNET DZMax Abort=0
UNET Convert EG Bridges=0
UNET Use Existing IB Tables=0
UNET Froude Limit=0
UNET Froude Power=0
Write IC File=0
Echo Input=False
Echo Output=False
Write Detailed=0

--- sgrtrcrk.f01 (steady flow) ---

Flow Title=NFF Regression Equation
Program Version=4.00
Number of Profiles=1
Profile Names=P100yr
River Rch & RM=sgrtrcrk,Main      ,3309.9
     360
River Rch & RM=sgrtrcrk,Main      ,2374.1
     384
River Rch & RM=sgrtrcrk,Main      ,1718.9
     412
Boundary for River Rch & Prof#=sgrtrcrk,Main      ,1
Up Type=0
Dn Type=3
Dn Slope=0.022234

--- sgrtrcrk.g01 (geometry) ---

Geom Title=USGS 10m DEM
Program Version=4.00

River Reach=sgrtrcrk        ,Main
Reach XY= 30
     1596368.304      253847.867     1596230.051      253799.699
     1596163.587      253757.706     1596112.994      253754.623
     1595873.426      253781.698     1595847.855      253770.882
     1595695.459      253780.143     1595588.094      253776.202
     1595326.265      253667.761     1595125.517      253646.808
     1594927.786       253577.77     1594747.086      253616.916
     1594634.262      253625.143     1594572.511       253590.78
     1594513.767      253573.773     1594476.781      253572.457
     1594219.498       253508.65     1594163.057      253462.065
     1594102.081      253372.078     1594014.012      253346.569
     1593971.478      253291.914      1593966.23      253266.958
     1593859.008      253190.131     1593825.793      253118.437
     1593803.767       253111.48     1593763.246      253138.419
     1593664.407      253137.297     1593504.365      253085.691
     1593467.411       253048.48     1593439.482      252938.558

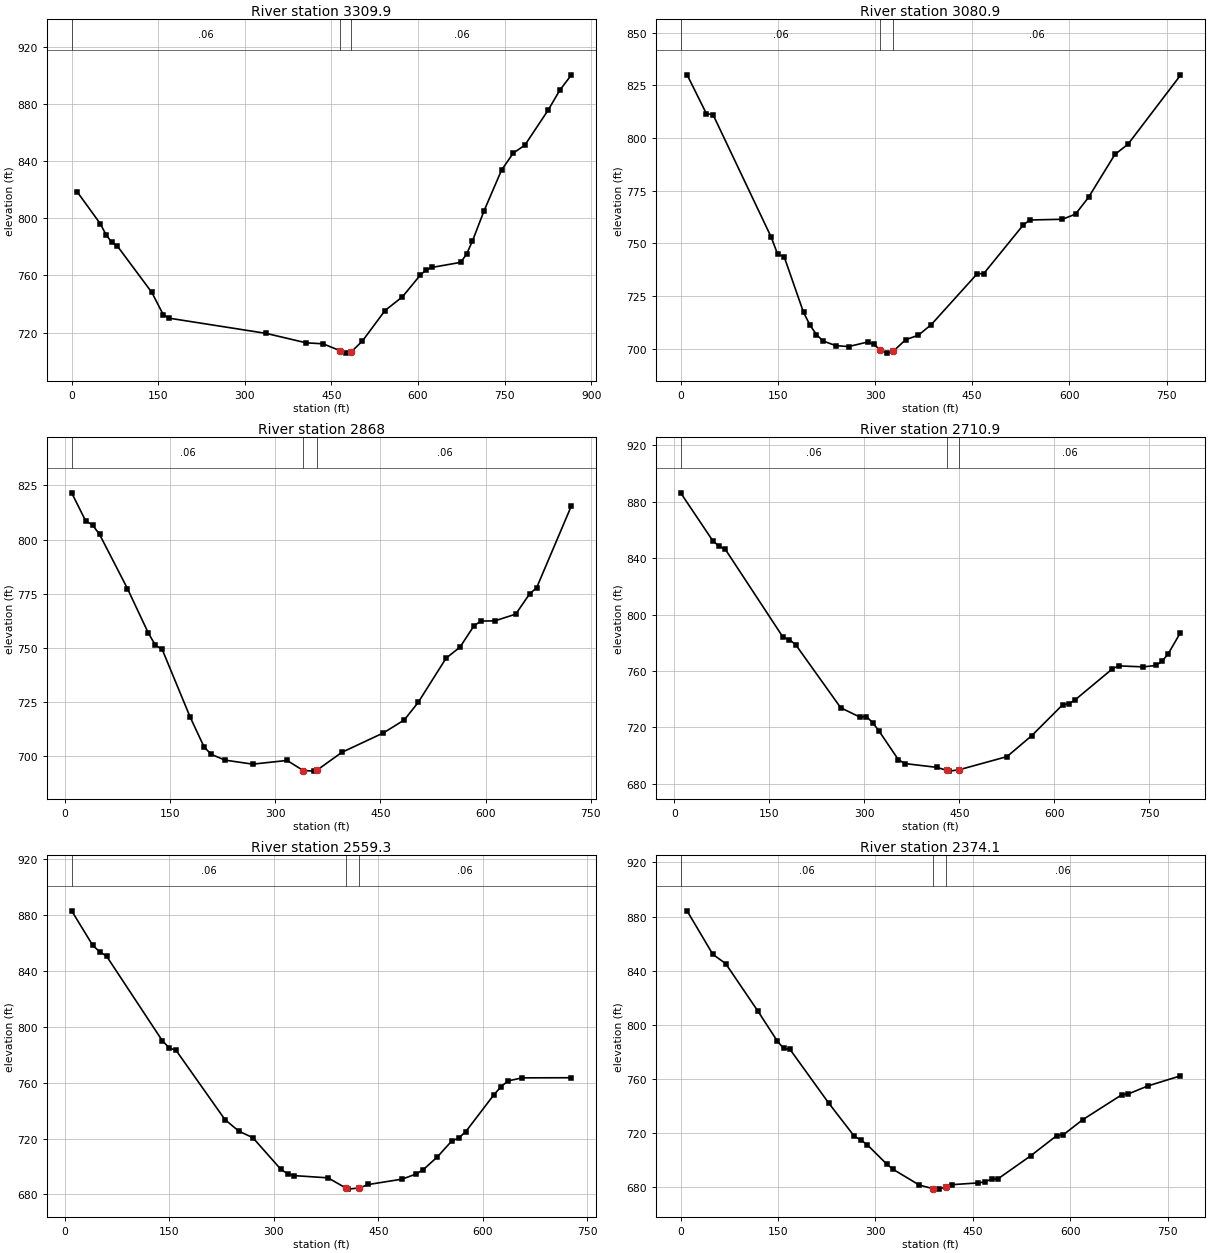
Type RM Length L Ch R = 1 ,3309.9  ,237.3,229,220.7
XS GIS Cut Line= 4
     1596664.514      253493.427     1596385.836      253775.531
     1596333.298      253901.164      1596404.11      254226.669
#Sta/Elev= 30
     9.9   818.3    49.6  796.19    59.5  788.52    69.4  783.21    79.3  780.48
   138.8  748.16   158.6  732.63   168.5  730.12   337.1  719.45   406.3  712.85
   435.4  712.17   464.4  707.46   474.4  705.65   484.4  706.56   503.5  714.04
   542.8  735.43   573.1  745.08   603.4  759.98   613.5  763.69   623.6  765.57
     674  769.16   684.1  774.95   694.2  783.98   714.4  805.23   744.7  833.69
   764.9  845.58   785.1  851.16   825.5   875.7   845.6  889.58   865.8  900.35
#Mann= 3 , 0 , 0
       0     .06       0   464.4    .045       0   484.4     .06       0
Bank Sta=464.4,484.4
XS Rating Curve= 0 ,0
Exp/Cntr=0.3,0.1

Type RM Length L Ch R = 1 ,3080.9  ,213,212.8,212.7
XS GIS Cut Line= 4
     1596134.569      253439.747     1596152.843       253688.73
     1596143.706      253815.505     1596220.228      254202.684
#Sta/Elev= 30
      10  829.97    39.9  811.45    49.9  811.12   139.8  752.88   149.8  744.72
   159.8  743.58   189.7  717.15   199.7  711.07   209.7   706.6   219.7   703.6
   239.7  701.34   259.4  700.93   288.8   703.1   298.5  701.91   308.1  699.35
   318.1  697.81   328.1  698.71   347.4  704.19     367  706.33   386.9  711.37
   457.7  735.49   467.8  735.56   528.6  758.58   538.7  761.03   589.3  761.38
   609.5  763.83   629.7  771.84   670.2  792.14   690.5  797.03   771.4  829.74
#Mann= 3 , 0 , 0
       0     .06       0   308.1    .045       0   328.1     .06       0
Bank Sta=308.1,328.1
XS Rating Curve= 0 ,0
Exp/Cntr=0.3,0.1

Type RM Length L Ch R = 1 ,2868    ,158.4,157.1,155.8
XS GIS Cut Line= 4
      1596005.51      253437.463     1595941.551      253697.867
     1595932.414      253844.058     1595994.088      254145.578
#Sta/Elev= 30
     9.9  821.54    29.8  808.62    39.7  806.72    49.7  802.34    89.4  777.39
   119.2  756.86   129.1  751.35     139  749.29   178.8  718.11   198.6  704.38
   208.6  700.97   228.4  698.25   268.1  696.39     317   698.1  340.06  693.44
     356  693.17  360.05  693.71   395.1  701.83   454.3   710.8   484.1  716.78
     504  724.91   543.7  745.29   563.5  750.35   583.4  760.19   593.3  762.37
   613.2  762.49     643  765.59   662.8  774.95   672.7  777.72   722.4  815.61
#Mann= 3 , 0 , 0
     9.9     .06       0  340.06    .045       0  360.05     .06       0
Bank Sta=340.06,360.05
XS Rating Curve= 0 ,0
Exp/Cntr=0.3,0.1

Type RM Length L Ch R = 1 ,2710.9  ,147.5,151.6,155.6
XS GIS Cut Line= 4
     1595667.441      253365.509     1595783.938       253688.73
     1595782.796      253870.327     1595870.739      254129.589
#Sta/Elev= 30
    10.1  886.42    60.6  852.59    70.7  848.54    80.8  846.22   171.8  783.93
   181.9  782.33     192  778.52   262.7     734     293  727.34   303.2  727.75
   313.3  723.37   323.4  717.32   353.7   697.2   363.8  694.39   414.2  691.69
  429.89  689.64   434.4  689.01  449.84     690   525.2  699.31   564.3  714.21
   613.2  736.15   622.9  736.85   632.7  739.56   691.4  761.52   701.2  763.68
   740.3  762.95   759.8  763.95   769.6  766.78   779.4  772.08   798.9  787.22
#Mann= 3 , 0 , 0
    10.1     .06       0  429.89    .045       0  449.84     .06       0
Bank Sta=429.89,449.84
XS Rating Curve= 0 ,0
Exp/Cntr=0.3,0.1

Type RM Length L Ch R = 1 ,2559.3  ,180.5,185.3,190
XS GIS Cut Line= 4
     1595651.452      253372.362     1595646.883      253692.156
     1595619.472      253854.337     1595569.219      254091.899
#Sta/Elev= 30
      10  882.81      40  858.34      50  853.55      60  850.47   139.9  790.08
   149.9  784.81   159.9     783   229.9  733.57   249.9  725.26   269.9  720.65
   309.8  698.17   319.8  694.74   329.5  693.48   377.9  691.89   403.2  684.66
   406.9  683.83  422.45  684.69   435.9  687.15   484.3  690.98   504.5  694.72
   514.7  697.86   534.9  706.96   555.1  718.14   565.2  720.36   575.4  724.88
   615.8  751.28     626  757.04   636.1   761.2   656.3  763.39   727.1  763.47
#Mann= 3 , 0 , 0
      10     .06       0   403.2    .045       0  422.45     .06       0
Bank Sta=403.2,422.45
XS Rating Curve= 0 ,0
Exp/Cntr=0.3,0.1

Type RM Length L Ch R = 1 ,2374.1  ,172.8,166.6,160.4
XS GIS Cut Line= 4
     1595628.609      253370.078      1595483.56      253652.182
      1595424.17      253813.221     1595400.185      254093.041
#Sta/Elev= 30
     9.9  884.22    49.6  852.07    69.4  845.22     119  810.16   148.7  788.18
   158.6   782.6   168.5  781.84     228  742.26   267.6  717.66   277.6  714.94
   287.5   711.4   317.2  697.25   327.3  693.27   367.7  681.64     388  679.12
     398  678.68     408  680.18   418.2  681.98   458.6  683.29   468.7  684.04
   478.8  686.11   488.9  686.34     539  703.24   579.1  718.17   589.2  718.77
   619.2  729.95   679.4  748.37   689.5     749   719.5  754.89   769.7  762.33
#Mann= 3 , 0 , 0
       0     .06       0     388    .045       0     408     .06       0
Bank Sta=388,408
XS Rating Curve= 0 ,0
Exp/Cntr=0.3,0.1

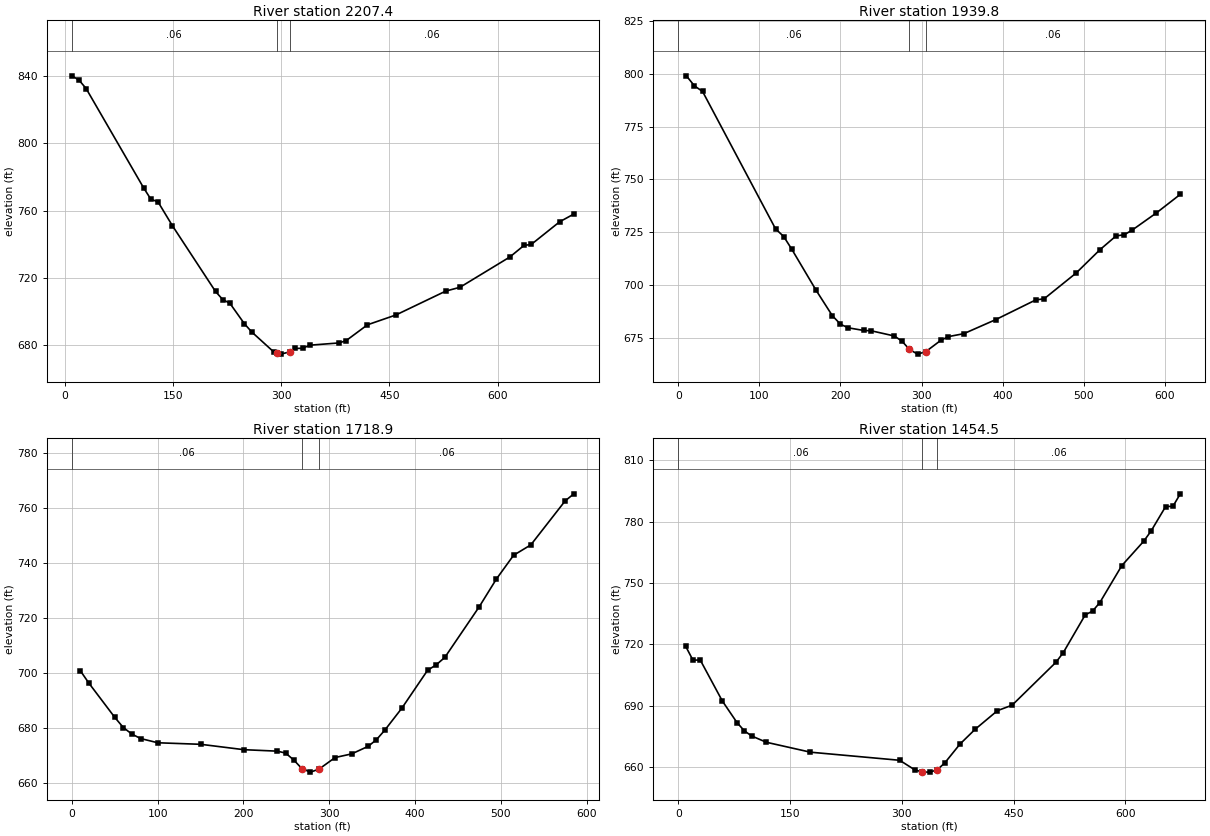
Type RM Length L Ch R = 1 ,2207.4  ,260.4,267.7,274.9
XS GIS Cut Line= 4
      1595386.48      253375.789     1595308.815      253601.928
     1595293.968      253742.409       1595354.5      254062.203
#Sta/Elev= 30
      10   840.2    19.9  837.73    29.9  832.63   109.6  773.53   119.6  766.82
   129.5  765.23   149.4  751.07   209.2  711.92   219.2   707.1   229.1   704.9
   249.2  692.74   259.3  687.87   289.6  676.06  293.78  675.43   299.6  674.64
  312.48     676   319.8  678.02   329.9  678.12     340  679.96   380.4   681.3
   390.2  682.66   419.8  692.09   459.3  697.95   528.3  712.14     548  714.41
   617.1  732.42   636.8  739.34   646.7  739.87   686.1  753.36   705.8  757.98
#Mann= 3 , 0 , 0
      10     .06       0  293.78    .045       0  312.48     .06       0
Bank Sta=293.78,312.48
XS Rating Curve= 0 ,0
Exp/Cntr=0.3,0.1

Type RM Length L Ch R = 1 ,1939.8  ,236.4,220.9,205.5
XS GIS Cut Line= 4
      1595160.34      253342.667     1595079.249      253525.406
     1595021.001      253665.887     1594989.021      253930.859
#Sta/Elev= 30
      10  799.02      20  794.26      30  791.61     120  726.54     130  722.95
   139.9  716.96   169.9  697.51   189.9   685.5   199.9  681.44   209.4  679.73
   228.4  678.48   237.9  678.31   266.5  675.84     276  673.31     285   669.5
     295  667.26     305  668.39   323.5  673.74     333  675.55     352  676.94
   391.5  683.62     441  692.98   450.9  693.41   490.4  705.63     520  716.75
   539.8  723.26   549.7  723.75   559.6  725.99   589.2  734.05   618.9  742.91
#Mann= 3 , 0 , 0
       0     .06       0     285    .045       0     305     .06       0
Bank Sta=285,305
XS Rating Curve= 0 ,0
Exp/Cntr=0.3,0.1

Type RM Length L Ch R = 1 ,1718.9  ,251.1,264.3,277.5
XS GIS Cut Line= 4
     1594827.316      253317.588      1594816.18      253537.732
     1594847.874      253678.213      1594859.01      253898.357
#Sta/Elev= 30
      10  700.94      20  696.42    50.1     684    60.1  680.29    70.1  677.92
    80.2  676.31   100.2  674.77   150.3  674.21   200.4  672.26   239.6  671.72
   249.2  671.01   258.8  668.46     268   665.4     278   664.1     288  665.18
   306.8  669.41     326  670.72   345.2  673.46   354.8  675.85   364.4  679.25
   384.5  687.33   414.5  701.11   424.6  703.11   434.6   705.8   474.6  724.17
   494.7   734.3   514.7  742.92   534.8   746.7   574.8  762.69   584.9  765.25
#Mann= 3 , 0 , 0
       0     .06       0     268    .045       0     288     .06       0
Bank Sta=268,288
XS Rating Curve= 0 ,0
Exp/Cntr=0.3,0.1

Type RM Length L Ch R = 1 ,1454.5  ,1430,1454.5,1479
XS GIS Cut Line= 4
     1594596.893      253267.049     1594604.602      253503.468
     1594550.637      253677.356     1594615.738      253924.054
#Sta/Elev= 30
     9.9  719.12    19.7  712.32    29.6  712.32    59.1  692.37    78.8   681.8
    88.7  677.74    98.6   675.2   118.3  672.14   177.4  667.29   297.2  663.33
   317.5  658.64   327.7  657.59   337.7  657.54   347.7   658.7   357.9  662.13
   378.2  671.29   398.4  678.47   428.4   687.6   448.1  690.28   506.9  711.25
   516.7  715.95   546.2  734.43     556  736.26   565.8  740.45   595.3  758.53
   624.7  770.45   634.5  775.39   654.1   787.4   663.9  787.52   673.8  793.62
#Mann= 3 , 0 , 0
       0     .06       0   327.7    .045       0   347.7     .06       0
Bank Sta=327.7,347.7
XS Rating Curve= 0 ,0
Exp/Cntr=0.3,0.1

Chan Stop Cuts=-1
Use User Specified Reach Order=0